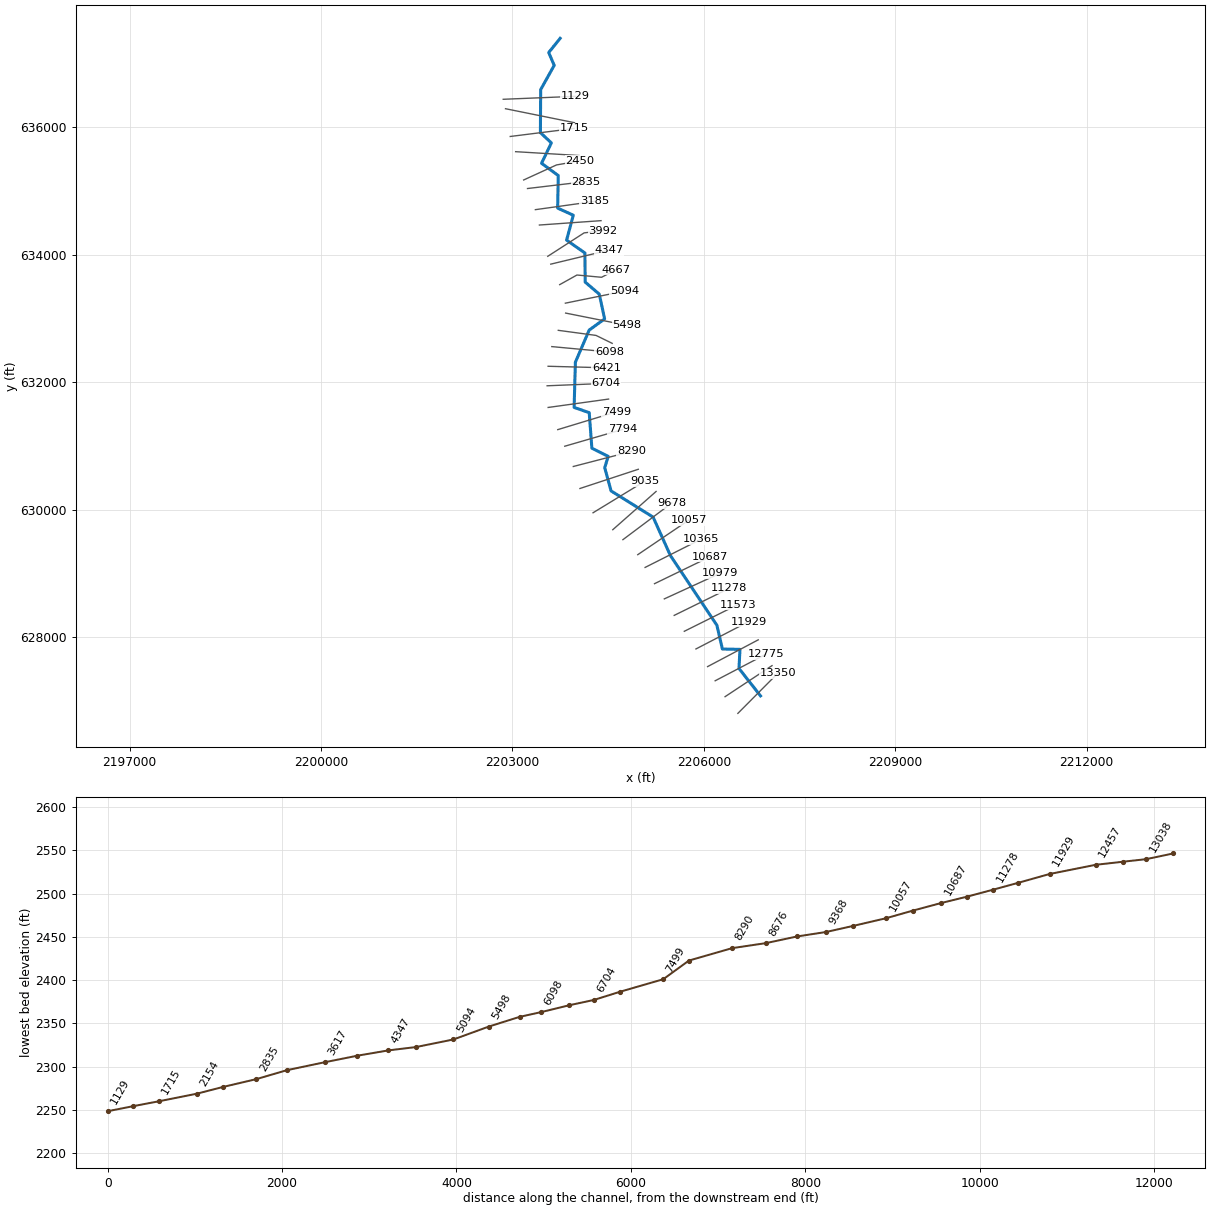
--- BEARCMPRN.prj (project) ---

Proj Title=BEARCMPRN
Current Plan=p01
Default Exp/Contr=0,0
English Units
Geom File=g01
Flow File=f01
Plan File=p01
BEGIN DESCRIPTION:
END DESCRIPTION:
DSS Export Rating Curves= 0
DSS Export Rating Curve Sorted= 0
DSS Export Volume Flow Curves= 0
DXF OffsetX= 0
DXF OffsetY= 0
DXF ScaleX= 0
DXF ScaleY= 0

--- BEARCMPRN.p01 (plan) ---

Plan Title=Floodplain
Program Version=4.00
Geom File=g01
Flow File=f01
K Sum by GR=0
Std Step Tol=0.01
Critical Tol=0.01
Num of Std Step Trials=20
Max Error Tol=0.3
Flow Tol Ratio=0.001
Split Flow NTrial=30
Split Flow Tol=0.02
Split Flow Ratio=0.02
Log Output Level=0
Friction Slope Method=1
Unsteady Friction Slope Method=2
Unsteady Bridges Friction Slope Method=1
Global Log Level=0
CheckData=False
Run HTab=0
Run UNet=0
Run PostProcess=0
UNET Theta=0
UNET Theta Warmup=0
UNET ZTol=0
UNET ZSATol=0
UNET MxIter=0
UNET MaxInSteps=0
UNET DtIC=0
UNET DtMin=0
UNET MaxCRTS=0
UNET WFStab=0
UNET SFStab=0
UNET WFX=0
UNET SFX=0
UNET DSS MLevel=0
UNET DZMax Abort=0
UNET Convert EG Bridges=0
UNET Use Existing IB Tables=0
UNET Froude Limit=0
UNET Froude Power=0
Write IC File=0
Echo Input=False
Echo Output=False
Write Detailed=0

--- BEARCMPRN.f01 (steady flow) ---

Flow Title=Flow
Program Version=4.00
Number of Profiles=1
Profile Names=P100yr
River Rch & RM=BEARCMPRN,Main      ,13401.1
208.0827
River Rch & RM=BEARCMPRN,Main      ,12901.1
300.5327
River Rch & RM=BEARCMPRN,Main      ,12401.1
304.3936
River Rch & RM=BEARCMPRN,Main      ,10901.1
336.8069
River Rch & RM=BEARCMPRN,Main      ,9901.1
356.3480
River Rch & RM=BEARCMPRN,Main      ,9401.1
395.5962
River Rch & RM=BEARCMPRN,Main      ,8401.1
408.4577
River Rch & RM=BEARCMPRN,Main      ,4901.1
507.1187
River Rch & RM=BEARCMPRN,Main      ,4901.1
453.2100
Boundary for River Rch & Prof#=BEARCMPRN,Main      ,1
Up Type=0
Dn Type=3
Dn Slope=0.020831

--- BEARCMPRN.g01 (geometry) ---

Geom Title=Geometry
Program Version=6.20

River Reach=BEARCMPRN       ,Main
Reach XY= 30
     2206889.098      627084.588     2206551.598      627513.755
     2206566.702      627813.234     2206291.381      627819.335
     2206205.418      628190.665     2205476.957      629283.993
     2205205.573       629886.54     2204546.592      630297.059
      2204447.03      630661.382     2204501.544      630838.119
     2204245.641      630966.591     2204203.974      631524.229
     2203967.298      631605.174     2203987.293      632314.486
      2204203.96      632818.652     2204445.627      632993.131
     2204361.599      633381.543     2204140.766      633570.085
     2204136.413      634026.676     2203849.303      634227.847
     2203954.421      634618.022     2203709.396      634729.941
      2203719.02      635239.484     2203457.037      635432.835
     2203610.596      635751.907      2203439.01      635912.953
      2203443.27      636587.439       2203655.5      636967.144
     2203569.021      637168.894     2203748.392      637390.825

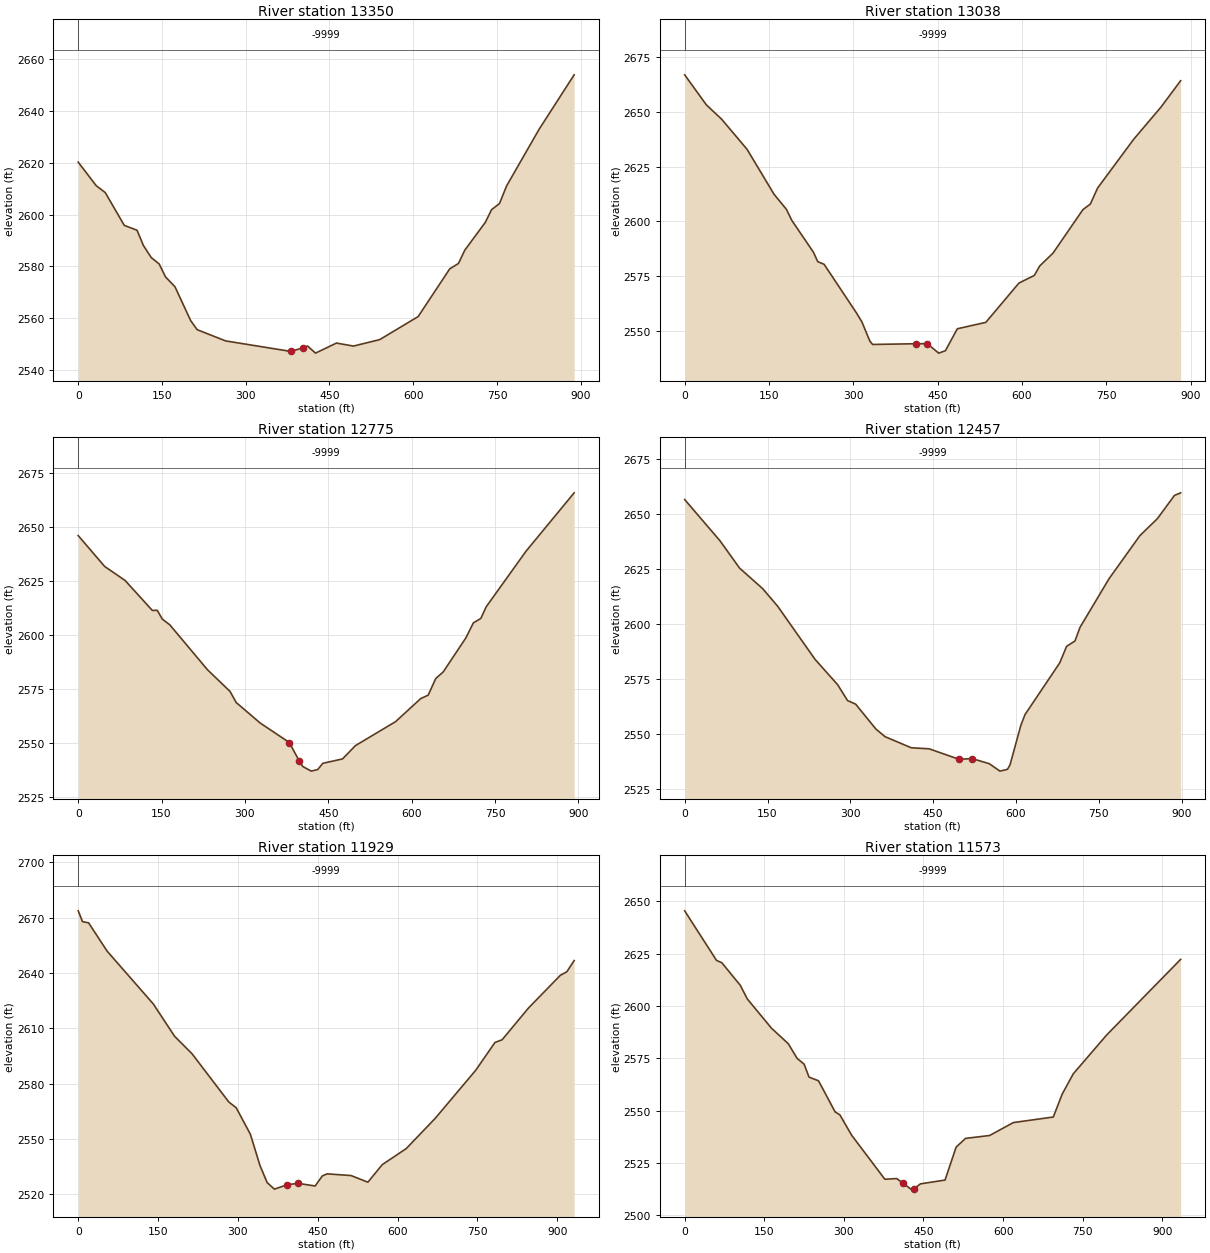
Type RM Length L Ch R = 1 ,13350   ,312.1,312.1,312.1
XS GIS Cut Line= 2
2206533.94533753626810.3936862682207160.50945685627439.999378981
#Sta/Elev= 30
       0 2620.26    32.1 2611.19    48.5 2608.49    82.5 2595.84   105.4 2593.96
   116.7 2588.09   130.8 2583.41     145 2580.94   156.3 2575.96   173.3 2572.14
   201.5 2559.04     213 2555.57     264 2551.23   381.3 2547.15   402.12548.562
   410.8 2549.25     425 2546.51   462.5  2550.4   492.9 2549.23     540 2551.73
   608.8 2560.62   665.4 2579.05   681.1 2581.15   692.4 2586.28     729 2596.97
   740.3  2601.9   754.5 2604.27   767.2 2611.07   825.4 2632.93   888.2 2653.97
#Mann= 1 ,-1,0
       0   -9999       0
Bank Sta=381.3,402.1
XS Rating Curve= 0 ,0
Exp/Cntr(USF)=0,0
Exp/Cntr=0.3,0.1

Type RM Length L Ch R = 1 ,13038   ,262.7,262.7,262.7
XS GIS Cut Line= 2
2206333.20149348627071.9689982162207069.26225501627558.620741376
#Sta/Elev= 30
       0 2666.93    38.5 2653.24    65.9 2646.63     111 2632.92   158.9 2612.44
     181 2605.52   190.6 2600.48   228.9 2586.01   236.8 2581.62   248.1 2580.41
   305.7  2558.2   315.3 2554.14   329.6  2545.3   334.4 2543.82   412.22544.153
   431.82544.167   451.9 2539.86   463.9 2540.96   485.1 2550.98   535.8 2553.91
   594.8 2571.87   622.1 2575.33   631.7 2579.66   655.4 2585.53   708.5 2605.36
   721.8 2607.93   734.7 2615.24   798.7 2637.44   847.5 2652.21   882.4 2664.23
#Mann= 1 ,-1,0
       0   -9999       0
Bank Sta=412.2,431.8
XS Rating Curve= 0 ,0
Exp/Cntr(USF)=0,0
Exp/Cntr=0.3,0.1

Type RM Length L Ch R = 1 ,12775   ,317.5,317.5,317.5
XS GIS Cut Line= 2
2206178.08125035627321.3780165852206968.89033298627735.031998271
#Sta/Elev= 30
       0 2645.88    47.5 2631.63    84.4 2625.11   133.3 2611.28   142.3  2611.3
   151.3 2607.27   164.9 2604.59   232.6 2583.84   273.2 2573.81   284.4 2568.65
   327.5 2559.18     3802550.161   397.52541.743   404.1 2539.09   419.3 2536.93
   431.1 2537.67   440.2 2540.55   475.6 2542.57   498.9 2548.73   571.1 2559.81
   616.3 2570.47   629.8 2572.07   643.4 2579.76   656.9 2582.82   697.9 2598.67
   711.1  2605.5   724.6 2607.57   734.2 2612.94   805.9 2638.66   892.5 2665.66
#Mann= 1 ,-1,0
       0   -9999       0
Bank Sta=380,397.5
XS Rating Curve= 0 ,0
Exp/Cntr(USF)=0,0
Exp/Cntr=0.3,0.1

Type RM Length L Ch R = 1 ,12457   ,528.4,528.4,528.4
XS GIS Cut Line= 2
2206059.45988795627543.4128744022206853.31054398627963.150002878
#Sta/Elev= 30
       0 2656.58    63.7 2637.94    99.5 2625.44   141.1 2616.17   168.2 2608.22
   236.1 2584.04   277.1  2572.5   294.9 2565.34   309.7 2563.69   346.1 2552.46
   362.9 2548.93   410.3 2543.91   442.8 2543.43   496.52538.713   520.72538.981
   551.5 2536.69   570.9 2533.31   584.5 2534.14     589 2536.07   608.6    2554
   616.2 2558.96   679.2 2582.48   691.5 2589.94   706.7 2592.38   715.7 2598.51
   768.4 2620.64   824.3 2640.21     856 2647.92   886.8 2658.44     898 2659.63
#Mann= 1 ,-1,0
       0   -9999       0
Bank Sta=496.5,520.7
XS Rating Curve= 0 ,0
Exp/Cntr(USF)=0,0
Exp/Cntr=0.3,0.1

Type RM Length L Ch R = 1 ,11929   ,355.9,355.9,355.9
XS GIS Cut Line= 2
2205876.96548427627820.1960533252206704.27344764628249.057901984
#Sta/Elev= 30
       0 2673.73     8.1 2667.87    19.5 2667.22    54.3 2651.86   141.2 2623.15
   181.1 2605.64   213.8 2596.18     283 2569.97   296.9 2566.84   323.6 2552.41
   341.5 2535.54     355 2526.23   368.6 2522.67   392.82525.037   412.62525.823
   445.2 2524.37   458.7 2529.82   467.7 2530.96   512.7 2530.04   544.3 2526.43
   571.3 2535.96   616.4 2544.68   670.8 2561.08     747 2587.21   783.1 2602.28
   796.6 2603.75   846.1 2620.98     906 2638.74   918.2 2640.67   931.9 2646.74
#Mann= 1 ,-1,0
       0   -9999       0
Bank Sta=392.8,412.6
XS Rating Curve= 0 ,0
Exp/Cntr(USF)=0,0
Exp/Cntr=0.3,0.1

Type RM Length L Ch R = 1 ,11573   ,294.5,294.5,294.5
XS GIS Cut Line= 2
2205694.47108058628096.9792322472206530.90376414628513.674787327
#Sta/Elev= 30
       0 2645.49      60 2621.83      70  2620.7   104.7 2609.96   118.1 2603.39
   163.6 2589.43   195.3 2582.01   211.9 2575.01   225.1 2572.26   234.3 2566.08
   252.2 2564.33   283.4  2549.5   292.4 2548.07   314.7 2538.31   377.2 2517.31
   399.6 2517.64   411.82515.349   426.4 2512.59   431.62512.677   444.3 2515.11
   490.6 2516.92   511.5 2532.65   529.2 2536.82   574.6  2538.2   619.4 2544.38
   694.6 2547.03   711.3 2557.93   732.2 2567.65   794.9 2586.13   934.5  2622.3
#Mann= 1 ,-1,0
       0   -9999       0
Bank Sta=411.8,431.6
XS Rating Curve= 0 ,0
Exp/Cntr(USF)=0,0
Exp/Cntr=0.3,0.1

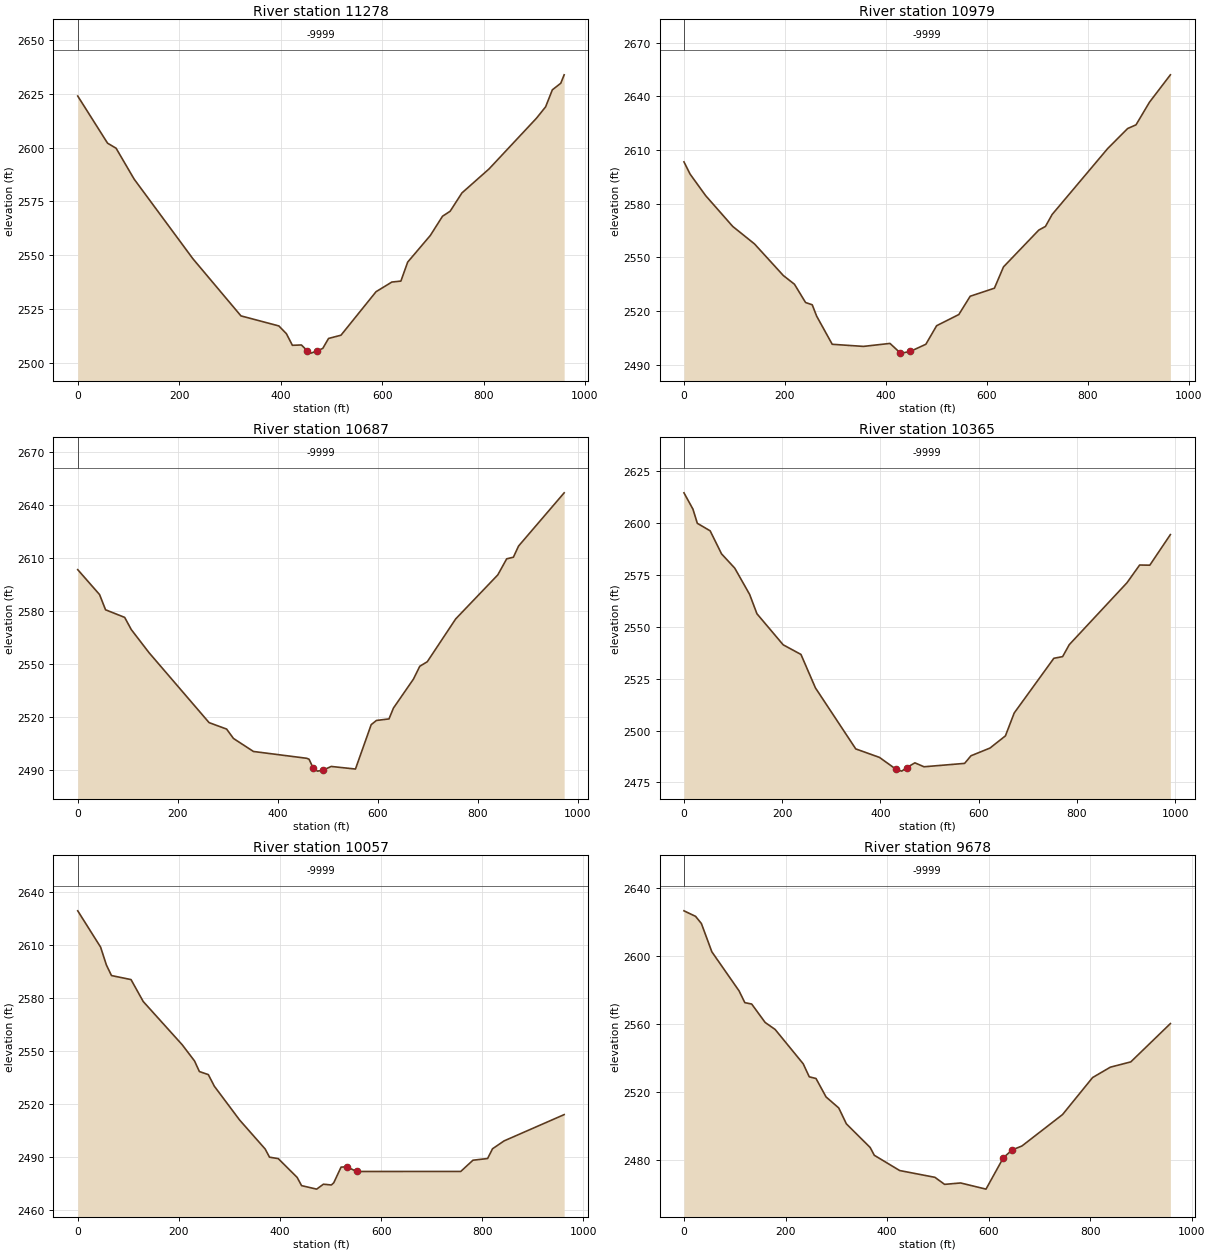
Type RM Length L Ch R = 1 ,11278   ,299.2,299.2,299.2
XS GIS Cut Line= 2
2205536.30926405628346.3882506162206397.07453477628769.166952486
#Sta/Elev= 30
       0 2623.94    58.8 2602.03    75.6 2599.69   111.3 2585.29   227.1  2548.3
   321.8 2521.76   396.5 2517.09   411.4 2513.48   423.2 2508.09     441 2508.24
   452.32505.586     460 2504.45   472.32505.551   483.1 2506.64   494.5 2511.27
     519 2512.78   588.1 2532.99   619.3 2537.49   637.1 2537.93   650.5 2546.75
   695.1 2559.13   719.2 2568.08   734.2 2570.39   757.4 2578.89   810.9 2590.06
   904.6 2613.68   922.5 2618.95   935.7 2626.82   952.3 2629.88     959  2633.8
#Mann= 1 ,-1,0
       0   -9999       0
Bank Sta=452.3,472.3
XS Rating Curve= 0 ,0
Exp/Cntr(USF)=0,0
Exp/Cntr=0.3,0.1

Type RM Length L Ch R = 1 ,10979   ,292.2,292.2,292.2
XS GIS Cut Line= 2
2205381.18902092 628604.921989172206257.16215861629006.409677277
#Sta/Elev= 30
       0  2603.3    12.1 2596.49    42.9 2584.45    96.6 2567.22   139.7 2557.45
   196.9 2539.75   218.9 2534.89   240.9 2524.68   254.1  2523.4   262.9 2517.04
   293.7 2501.32   355.5 2500.14   408.1 2501.81   428.12496.604   430.9 2496.38
   448.12497.296   479.2 2501.34   500.5  2511.7   544.5 2517.96     567 2528.18
     615 2532.68     633  2544.6   702.9 2565.17   716.1 2567.21   729.3 2573.88
   839.3 2610.73   878.9 2621.95   895.5 2624.01   922.2 2636.68   963.6 2651.97
#Mann= 1 ,-1,0
       0   -9999       0
Bank Sta=428.1,448.1
XS Rating Curve= 0 ,0
Exp/Cntr(USF)=0,0
Exp/Cntr=0.3,0.1

Type RM Length L Ch R = 1 ,10687   ,321.8,321.8,321.8
XS GIS Cut Line= 2
2205227.70033587 628843.295509822206103.67347356629267.594998388
#Sta/Elev= 30
       0 2603.25    43.7 2589.13    55.7 2580.51    93.9 2576.22   107.2 2569.29
   142.5 2556.28   262.8 2516.61   297.9 2512.95   311.6 2507.63   351.6 2500.26
   458.3  2496.4   462.9 2495.86   471.52490.628   479.7 2489.13   490.52489.644
   507.2 2491.78   555.7 2490.31   587.2 2515.46   597.6 2517.82   622.8 2518.71
   631.7 2524.84   671.7 2541.25   684.4 2548.52   699.4 2551.09   756.3 2575.36
   840.5 2600.28   858.3 2609.39   871.7  2610.3   882.1 2616.63   973.3 2646.77
#Mann= 1 ,-1,0
       0   -9999       0
Bank Sta=471.5,490.5
XS Rating Curve= 0 ,0
Exp/Cntr(USF)=0,0
Exp/Cntr=0.3,0.1

Type RM Length L Ch R = 1 ,10365   ,308.1,308.1,308.1
XS GIS Cut Line= 2
2205079.87986889629097.8752029612205964.06525474 629544.07401997
#Sta/Elev= 30
       0  2614.5    18.3 2606.63    27.2 2599.82    53.3  2596.2    76.5  2585.1
   103.4 2578.22   133.7 2565.56   148.6 2556.24     202 2541.28   238.2 2536.65
   267.7 2520.52   349.8 2491.13     398 2487.05   432.22481.263   443.4 2480.43
   453.32482.075   470.2 2484.43   488.7 2482.53   571.4 2484.16   584.4 2487.83
   623.1 2491.54   654.5 2497.41   672.4 2508.43   753.1 2534.79     771 2535.59
   784.4 2541.32     902 2571.17   927.8 2579.72   948.5 2579.64   990.4 2594.38
#Mann= 1 ,-1,0
       0   -9999       0
Bank Sta=432.2,453.3
XS Rating Curve= 0 ,0
Exp/Cntr(USF)=0,0
Exp/Cntr=0.3,0.1

Type RM Length L Ch R = 1 ,10057   ,379.2,379.2,379.2
XS GIS Cut Line= 2
2204964.90839457629297.7065749962205761.49646665629836.977537885
#Sta/Elev= 30
       0 2629.33    45.2 2608.77    56.7 2598.63    66.7 2592.65   105.4 2590.36
   129.5 2577.94   206.5 2553.46     231 2544.23   240.6 2538.24   258.3  2536.5
   270.2 2529.91   320.1 2510.79   370.7 2494.33   379.3  2489.7   396.6 2488.89
   433.9 2478.26   442.7 2473.58   472.5  2471.6   485.9 2474.39   501.5 2473.95
   506.3 2475.18   520.8 2484.07   532.4 2484.25   551.42481.599   757.5 2481.62
   781.6 2487.98   810.6 2488.94   820.3 2494.46   843.1 2498.92     962 2513.83
#Mann= 1 ,-1,0
       0   -9999       0
Bank Sta=532.4,551.4
XS Rating Curve= 0 ,0
Exp/Cntr(USF)=0,0
Exp/Cntr=0.3,0.1

Type RM Length L Ch R = 1 ,9678    ,310.2,310.2,310.2
XS GIS Cut Line= 2
2204732.22802987629533.1243557492205498.70452535630107.981727357
#Sta/Elev= 30
       0 2626.29    22.9 2623.03    34.3 2618.84    54.9 2602.21   108.6  2579.2
   119.9  2572.3   133.4 2571.49   159.9 2560.66   179.5 2556.56   234.9 2536.34
   246.8  2528.7   260.1  2527.7   279.9 2516.86   304.9 2510.38   319.9 2501.04
   366.8 2487.13   374.9 2482.56   424.9 2473.59   494.3  2469.6   513.4 2465.46
   544.9 2466.28   594.9 2462.66   629.12481.119   646.62485.743   665.7 2488.02
   745.7 2506.51   804.9 2528.27   839.9 2534.37   880.1 2537.47   958.1 2559.99
#Mann= 1 ,-1,0
       0   -9999       0
Bank Sta=629.1,646.6
XS Rating Curve= 0 ,0
Exp/Cntr(USF)=0,0
Exp/Cntr=0.3,0.1

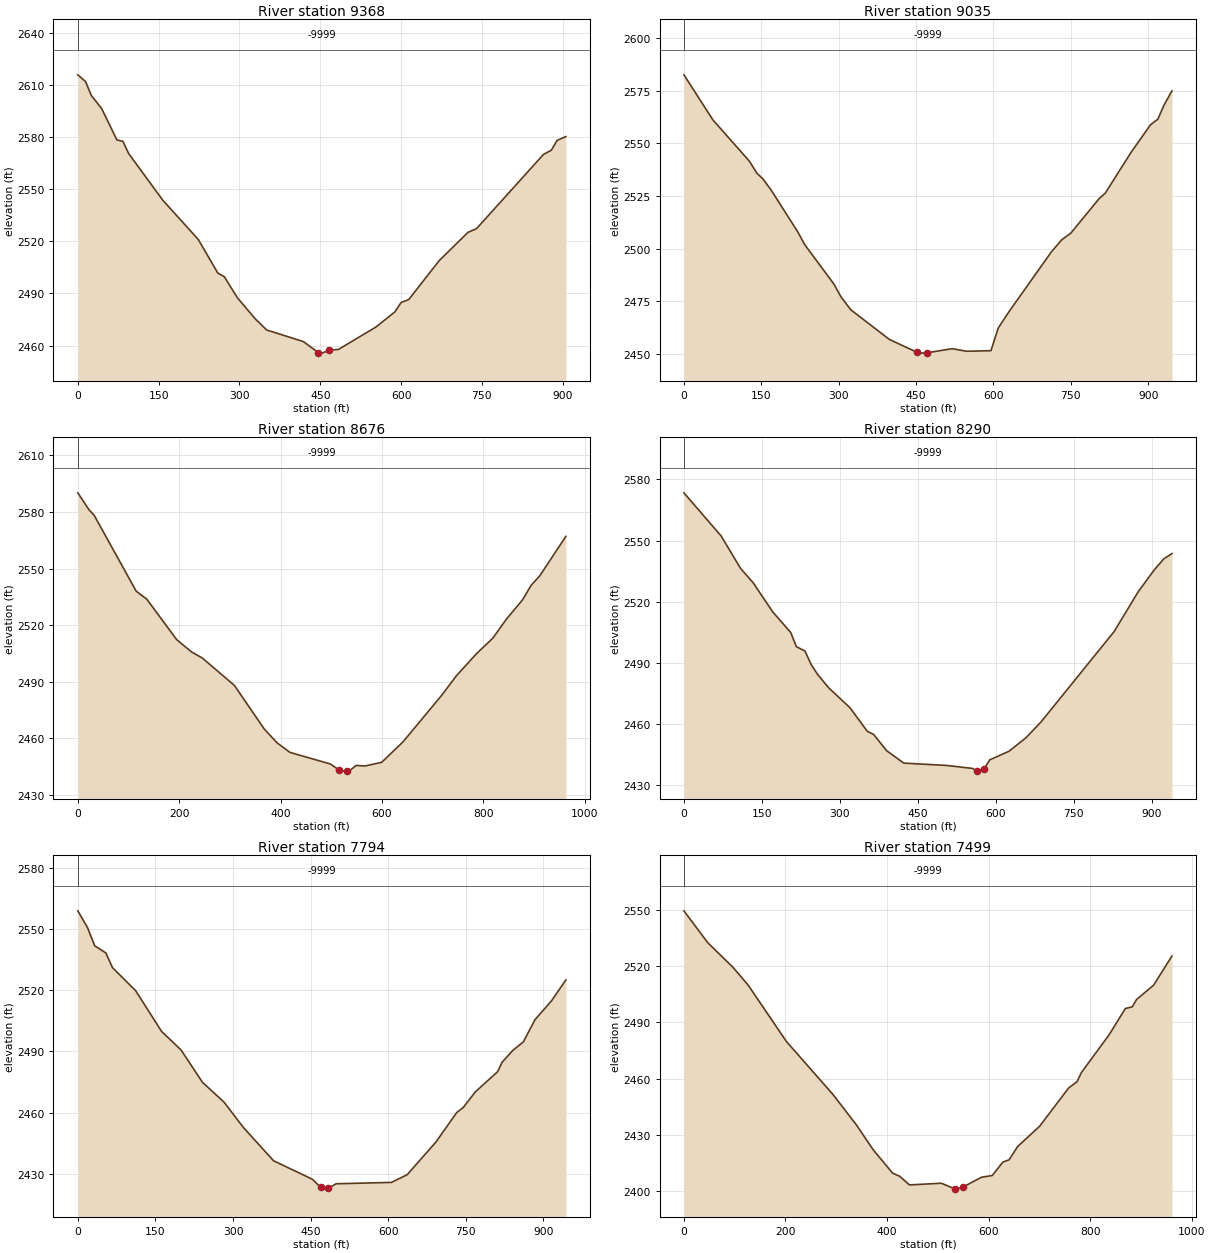
Type RM Length L Ch R = 1 ,9368    ,332.6,332.6,332.6
XS GIS Cut Line= 2
2204573.45789866  629689.15707092205252.33708037630288.651187005
#Sta/Elev= 30
       0 2615.87    14.3 2612.04      25 2604.04    44.4 2596.36    72.5  2578.4
    83.7 2577.55    94.3 2570.58   157.8 2543.63   223.6 2521.05   259.8 2501.74
     272 2499.58   296.1 2487.51   329.1 2475.42   350.5 2468.94   418.5 2462.28
   446.32455.951   453.3 2455.62   466.72457.294   483.7 2457.75   553.3 2470.67
   588.6 2479.41   599.9 2484.77   614.1 2486.47   670.7  2508.9     724 2525.16
     740 2527.32   864.2 2570.05   878.8 2572.47   889.5 2578.14   905.7 2580.31
#Mann= 1 ,-1,0
       0   -9999       0
Bank Sta=446.3,466.7
XS Rating Curve= 0 ,0
Exp/Cntr(USF)=0,0
Exp/Cntr=0.3,0.1

Type RM Length L Ch R = 1 ,9035    ,359.1,359.1,359.1
XS GIS Cut Line= 2
2204264.12988442629954.6864282622205071.66762072630447.421318211
#Sta/Elev= 30
       0  2582.5    56.3 2561.08   126.6 2541.62   141.5 2535.83   153.2 2533.11
   168.7 2527.97   220.3 2508.15   234.3 2501.88   290.6 2483.29   304.6 2477.11
   323.4 2471.04   398.3 2456.95   452.52450.792   459.3 2450.46     4712450.606
   519.9 2452.57   548.3 2451.34   595.2 2451.62   609.2 2462.32   630.4 2470.22
   711.9 2498.37   732.3 2504.24   749.8 2507.34     805 2523.82   816.7 2526.35
   866.9 2545.77   904.4  2558.8   918.7 2561.47   930.2 2567.95     946  2574.9
#Mann= 1 ,-1,0
       0   -9999       0
Bank Sta=452.5,471
XS Rating Curve= 0 ,0
Exp/Cntr(USF)=0,0
Exp/Cntr=0.3,0.1

Type RM Length L Ch R = 1 ,8676    ,386.2,386.2,386.2
XS GIS Cut Line= 2
2204058.82368027630335.1872599452204973.12064273630636.303026025
#Sta/Elev= 30
       0 2590.14    22.5    2581    31.9 2578.41   115.1 2538.06   136.2 2533.76
   195.1 2512.33   224.6 2505.81   245.7 2502.61   308.9  2488.1   367.8 2464.99
   393.1 2457.68   418.3 2452.65   498.4 2446.47   514.82443.368   522.2 2442.71
   530.42442.751   536.3 2442.97   548.9 2445.72   566.6 2445.44   599.4 2447.39
   641.5 2458.24   717.4 2482.79   746.8 2493.25   786.4 2504.95   818.4  2513.1
   845.3 2523.21   877.4 2533.53   894.2 2541.19   911.1 2546.16   962.6 2567.06
#Mann= 1 ,-1,0
       0   -9999       0
Bank Sta=514.8,530.4
XS Rating Curve= 0 ,0
Exp/Cntr(USF)=0,0
Exp/Cntr=0.3,0.1

Type RM Length L Ch R = 1 ,8290    ,495.5,495.5,495.5
XS GIS Cut Line= 2
2203954.80187017630680.1016829092204863.62400052630915.519463663
#Sta/Elev= 30
       0 2573.38    71.7  2552.2   108.9 2536.35   133.3 2529.25   170.8 2515.04
   205.5 2504.89   216.3 2497.95   232.8 2495.83   245.2 2489.01   257.6 2484.21
   279.2 2477.59   319.6 2467.98   352.6 2456.48     365 2454.91   389.8 2446.99
   422.9 2440.86   505.5 2439.72   555.1 2438.26   563.4 2436.93   564.32437.013
   576.72437.743   588.2 2442.44   625.4 2446.69   658.3 2453.36   687.3 2461.16
   827.8 2505.43   873.3 2524.65   904.5 2535.52   922.9 2540.96   938.8  2543.6
#Mann= 1 ,-1,0
       0   -9999       0
Bank Sta=564.3,576.7
XS Rating Curve= 0 ,0
Exp/Cntr(USF)=0,0
Exp/Cntr=0.3,0.1

Type RM Length L Ch R = 1 ,7794    ,295.7,295.7,295.7
XS GIS Cut Line= 2
2203820.66848346630997.6419453212204726.75319776631260.433886628
#Sta/Elev= 30
       0 2558.83    18.6  2550.7    32.8 2541.67    54.1 2538.23      67 2531.04
   111.9 2519.68   161.9 2499.81   199.4 2490.75     241 2474.86   282.7 2465.13
   320.2  2452.7   378.5 2436.43   453.5 2427.39   469.42423.451   478.4 2422.56
   484.12422.967   499.3 2425.18   606.2 2425.86   636.7 2429.63   692.2  2445.6
   732.5 2460.07     745 2462.52   768.4 2470.18   811.6 2480.09     820 2484.63
   840.8 2490.46   861.2 2494.65   883.8 2505.55   915.8 2514.81   943.4 2524.99
#Mann= 1 ,-1,0
       0   -9999       0
Bank Sta=469.4,484.1
XS Rating Curve= 0 ,0
Exp/Cntr(USF)=0,0
Exp/Cntr=0.3,0.1

Type RM Length L Ch R = 1 ,7499    ,492.5,492.5,492.5
XS GIS Cut Line= 2
2203711.17184125631257.6964705722204630.94363582 631536.91290821
#Sta/Elev= 30
       0 2549.55      47 2532.52    96.6 2519.39   126.5  2509.9   201.7 2479.83
   293.7 2451.43   339.6 2435.27   373.1 2421.81   410.9 2409.51   425.1 2407.77
   444.2 2403.16   506.9 2404.07   533.72401.052   536.1 2400.92   548.9 2401.93
   586.3 2407.29   607.2 2408.18   628.1 2415.34   640.6 2416.61   657.3 2423.68
   700.5 2434.48   757.7 2454.93   774.4 2458.36   782.8 2463.17   837.4 2483.34
   869.4 2497.37   883.1 2498.28   891.4 2502.18   924.9 2509.79   961.2 2525.43
#Mann= 1 ,-1,0
       0   -9999       0
Bank Sta=533.7,548.9
XS Rating Curve= 0 ,0
Exp/Cntr(USF)=0,0
Exp/Cntr=0.3,0.1

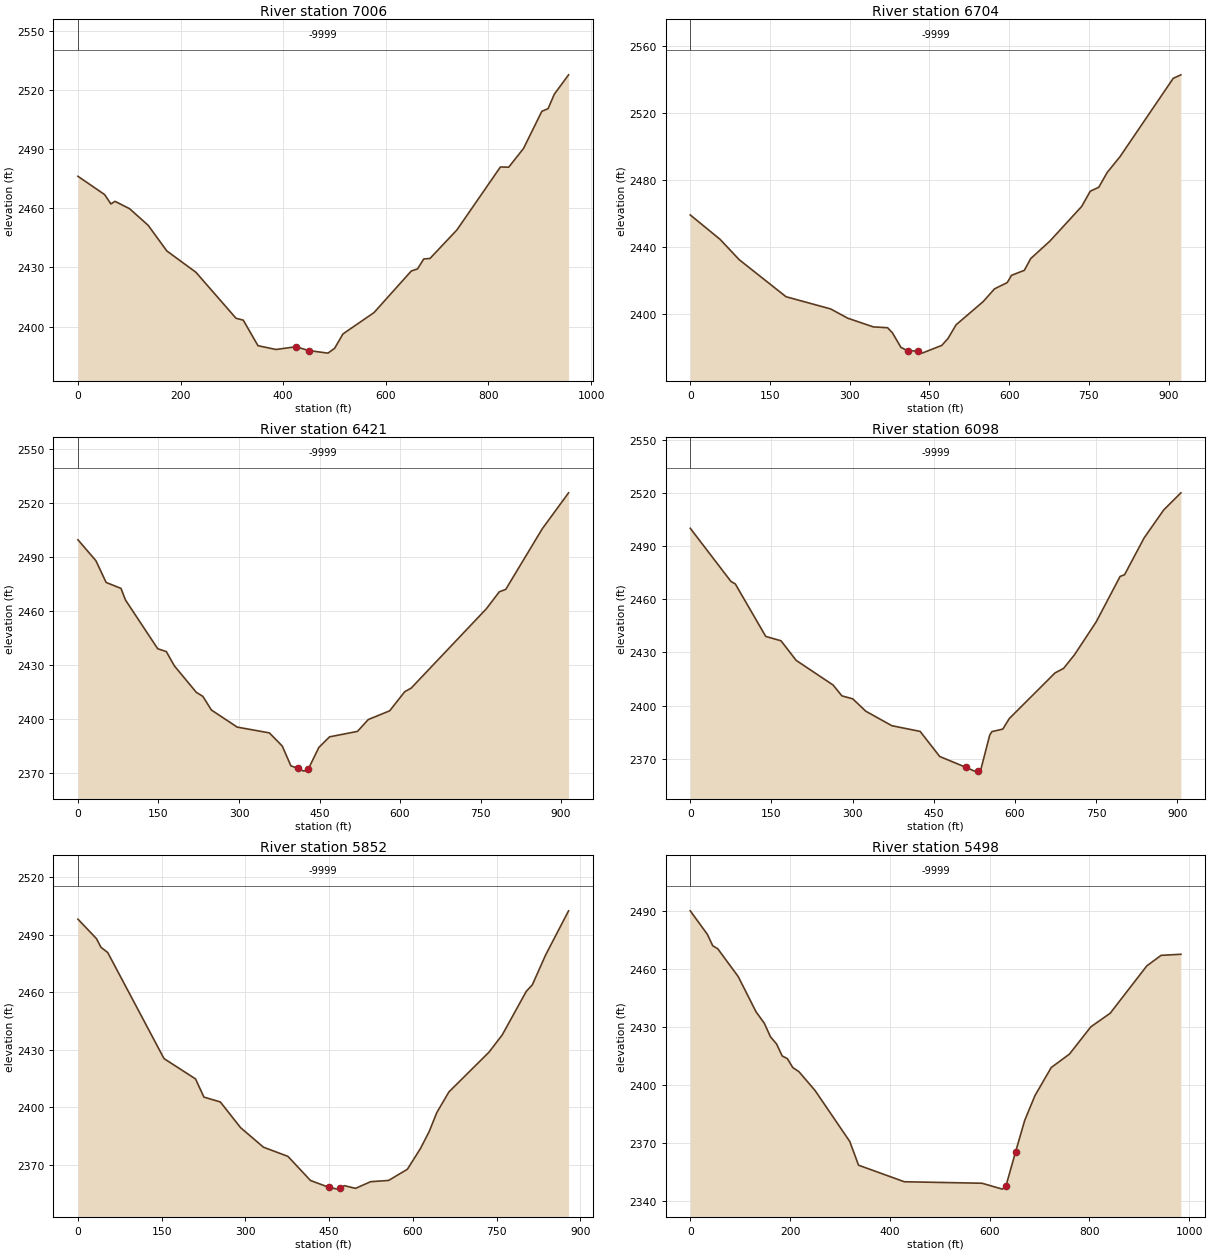
Type RM Length L Ch R = 1 ,7006    ,302.6,302.6,302.6
XS GIS Cut Line= 2
2203560.61395821631605.3483095922204507.75991334631736.744280246
#Sta/Elev= 30
       0 2476.24    52.1 2466.95    64.2  2462.2    72.2 2463.53   100.5 2459.82
   136.9 2451.37   173.2 2438.38     230 2427.54     308 2404.23   322.2 2403.26
   350.9  2390.3     386 2388.38     4252389.768   449.52387.846   487.3 2386.53
   500.3 2388.99   516.5 2396.27     577 2407.09   649.7  2428.2   661.8 2429.25
     674 2434.31   686.1 2434.55   738.6 2449.03   823.4 2480.98   839.5 2480.84
   868.3 2490.32   904.1  2509.2   916.3 2510.56   928.4 2517.89   956.2 2527.71
#Mann= 1 ,-1,0
       0   -9999       0
Bank Sta=425,449.5
XS Rating Curve= 0 ,0
Exp/Cntr(USF)=0,0
Exp/Cntr=0.3,0.1

Type RM Length L Ch R = 1 ,6704    ,282.2,282.2,282.2
XS GIS Cut Line= 2
2203544.14871363631944.9571291452204466.54842762631982.651348226
#Sta/Elev= 30
       0 2459.29    56.1 2444.75    92.1 2432.63   180.2 2410.57   264.2 2403.29
   296.3 2397.78   344.3 2392.61   371.3  2392.1   380.3 2389.13   396.4  2380.4
   408.82378.428   428.72378.203   436.4 2376.97   473.3 2381.58   484.9 2385.64
   500.2 2393.85   550.8 2407.56   572.5 2415.24   596.5 2419.01   604.5 2423.31
   628.6 2426.29   640.6 2433.28   676.6 2443.66   736.6 2464.38   752.7 2473.43
   768.7 2475.78   784.5 2484.57   808.7    2494   908.8 2540.65   923.2 2542.74
#Mann= 1 ,-1,0
       0   -9999       0
Bank Sta=408.8,428.7
XS Rating Curve= 0 ,0
Exp/Cntr(USF)=0,0
Exp/Cntr=0.3,0.1

Type RM Length L Ch R = 1 ,6421    ,323.4,323.4,323.4
XS GIS Cut Line= 2
2203559.66986266632250.9454958042204473.20034863632226.555118751
#Sta/Elev= 30
       0 2499.54    33.4 2487.94    52.5 2475.82    80.2  2472.5    88.5 2466.06
   148.6 2438.93   164.6 2437.37   179.6 2429.41   220.6 2414.64   232.6 2412.47
   248.6 2404.85   296.6 2395.35   356.6 2392.12   380.6  2384.8   396.6 2373.82
   409.12372.408   420.7 2370.85   429.32372.121   448.7 2384.03   468.7 2389.93
   520.7 2392.95   540.7 2399.53   580.7 2404.41   608.7 2415.03   620.7 2417.02
   760.8 2461.18   784.8  2470.6   796.8 2471.93   864.8 2505.61   913.9 2525.67
#Mann= 1 ,-1,0
       0   -9999       0
Bank Sta=409.1,429.3
XS Rating Curve= 0 ,0
Exp/Cntr(USF)=0,0
Exp/Cntr=0.3,0.1

Type RM Length L Ch R = 1 ,6098    ,245.7,245.7,245.7
XS GIS Cut Line= 2
2203617.31984479632559.1511694672204519.76379573632474.893503286
#Sta/Elev= 30
       0 2500.28    75.2 2470.18    83.2  2468.8   139.5 2439.07   167.6 2436.64
   195.7 2425.53     264 2411.56   280.1 2405.47   300.2 2403.78   324.4 2396.75
   372.5 2388.57   424.7 2385.36   460.9 2371.15     5102364.938   525.1 2362.88
   530.82362.981   537.2 2364.24   553.3 2383.31   557.3 2385.23   577.4 2386.66
   589.4 2392.62   673.8 2418.41   689.8 2421.04     710 2428.77   750.1  2447.4
   794.1 2473.03   802.3 2473.97   838.5 2494.82   874.6 2510.61   906.4 2520.32
#Mann= 1 ,-1,0
       0   -9999       0
Bank Sta=510,530.8
XS Rating Curve= 0 ,0
Exp/Cntr(USF)=0,0
Exp/Cntr=0.3,0.1

Type RM Length L Ch R = 1 ,5852    ,353.8,353.8,353.8
XS GIS Cut Line= 3
2203719.31596701632814.1414750162204311.33693728632734.318422844
2204564.10993583632610.149230577
#Sta/Elev= 30
       0 2498.19    33.2 2488.03    41.2 2483.53    53.3 2480.82   154.2 2425.49
   210.7 2414.88   225.7 2405.41   255.1 2402.88   291.5 2389.44   332.4 2379.28
   376.2 2374.51   416.6 2361.92   449.8 2358.34     465 2357.42   470.22358.035
   477.1 2359.23   497.3 2357.82   524.4  2361.3   556.5 2361.94   590.2 2367.77
   613.8 2378.68   629.5 2387.58   642.9 2397.32   664.6 2408.09   736.5 2428.86
   760.2 2437.86   803.3 2460.58     814 2463.91   837.9 2479.53     879 2502.54
#Mann= 1 ,-1,0
       0   -9999       0
Bank Sta=449.8,470.2
XS Rating Curve= 0 ,0
Exp/Cntr(USF)=0,0
Exp/Cntr=0.3,0.1

Type RM Length L Ch R = 1 ,5498    ,404.1,404.1,404.1
XS GIS Cut Line= 2
2203834.61593125633084.6529295982204799.14447833632891.747220183
#Sta/Elev= 30
       0 2489.84    34.2 2477.74    45.1  2471.8    55.3 2470.21    96.1 2455.92
   132.1 2437.61   148.4 2431.84   160.7 2424.85   172.9 2421.15   184.4 2414.89
   194.6 2413.55   205.6 2408.91   217.8 2406.83   250.4 2397.01   319.8 2370.76
   337.4 2358.51   429.2 2349.97   584.9  2349.2   625.7 2346.16   632.62347.527
   652.12365.319   670.5 2381.64   690.9 2394.37   723.6 2408.91   760.3  2415.9
   803.1 2429.96   841.9 2436.97   915.3 2461.42   943.9 2466.85   983.6 2467.41
#Mann= 1 ,-1,0
       0   -9999       0
Bank Sta=632.6,652.1
XS Rating Curve= 0 ,0
Exp/Cntr(USF)=0,0
Exp/Cntr=0.3,0.1

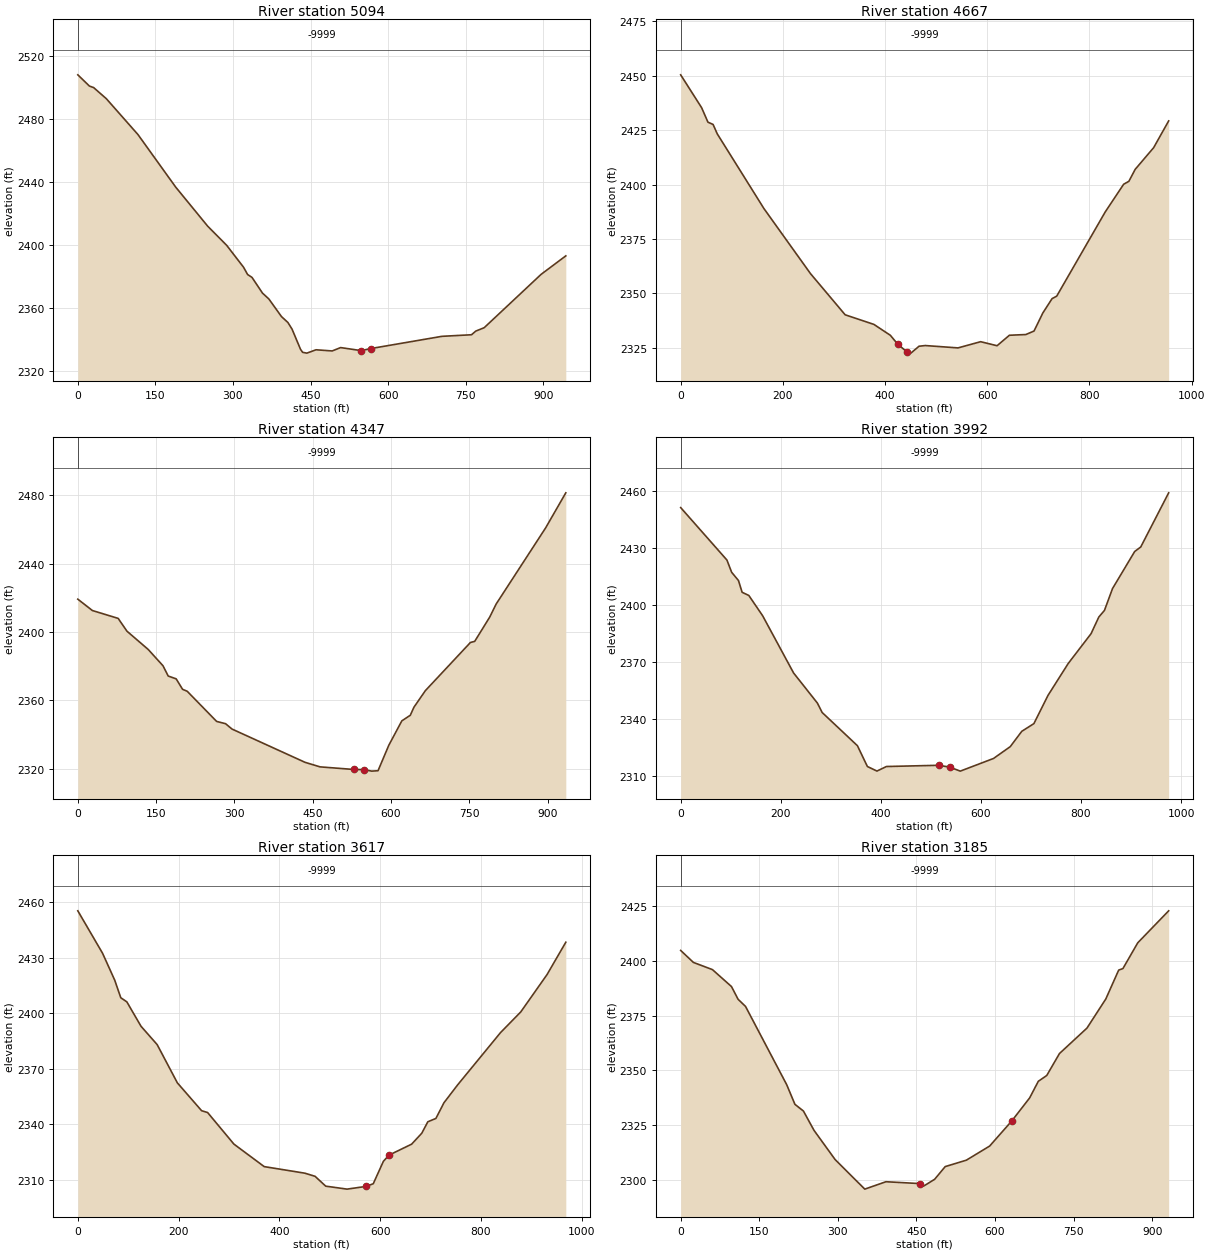
Type RM Length L Ch R = 1 ,5094    ,427.7,427.7,427.7
XS GIS Cut Line= 2
2203830.18131725633239.8644199322204754.79833824633428.335515338
#Sta/Elev= 30
       0 2507.89    22.4 2500.77    30.6 2499.79    55.1 2492.76   116.3 2469.99
   189.3 2436.63   251.1 2411.86   287.8 2399.72   320.5 2385.79   328.3 2381.18
   336.8 2379.35   357.2 2369.33   369.4 2365.66   393.9 2354.45   406.2 2350.74
   414.3 2346.49   430.7 2333.67   434.8 2331.79   442.9 2331.29   460.6 2333.41
   491.9 2332.67   508.2 2334.81   547.9 2332.88     5672334.216   704.2 2341.95
   761.3 2342.95   769.5 2345.27   785.8 2347.43     896 2381.32   943.6 2393.01
#Mann= 1 ,-1,0
       0   -9999       0
Bank Sta=547.9,567
XS Rating Curve= 0 ,0
Exp/Cntr(USF)=0,0
Exp/Cntr=0.3,0.1

Type RM Length L Ch R = 1 ,4667    ,319.5,319.5,319.5
XS GIS Cut Line= 4
2203741.48903705633530.3316375572204012.00049164633681.108513882
2204397.81191047633645.6316018052204626.19453196633765.366180063
#Sta/Elev= 30
       0  2450.4      41  2435.3    53.4 2428.64    63.4 2427.61    71.7 2423.24
   162.9 2388.97     254 2359.08   321.9 2340.15   378.2 2335.73   410.3 2330.74
   424.82326.647   443.62322.956   450.5 2322.54   466.5 2325.71   478.6 2326.02
   542.8 2324.94     587 2327.79   619.2 2325.94   643.3 2330.75   675.4 2331.08
   691.5 2332.68   708.8    2341   726.9 2347.59   735.9 2348.72   830.8 2387.38
   866.9 2400.13   877.1 2401.47   889.5 2406.98   925.6 2416.93     955 2429.22
#Mann= 1 ,-1,0
       0   -9999       0
Bank Sta=424.8,443.6
XS Rating Curve= 0 ,0
Exp/Cntr(USF)=0,0
Exp/Cntr=0.3,0.1

Type RM Length L Ch R = 1 ,4347    ,355.4,355.4,355.4
XS GIS Cut Line= 2
2203601.03881373633851.4668247062204509.86094408634070.460109128
#Sta/Elev= 30
       0 2419.19    27.9 2412.54    77.3 2407.94    94.1 2400.47   134.9 2389.76
   163.2 2380.23   173.1 2374.24   188.4 2372.58   200.7 2366.46   209.6 2365.31
   265.9 2347.69     283 2346.36   295.4 2343.22   435.2 2323.78     464 2321.11
   529.52319.572   548.52319.526   562.8 2318.62   575.1 2318.85   595.7 2333.72
   620.7 2348.02   636.9 2351.29   643.9    2356   665.7 2365.66   752.1 2393.85
   760.3  2394.5   789.1 2408.73   801.4 2416.35   896.1 2460.84   934.8 2481.37
#Mann= 1 ,-1,0
       0   -9999       0
Bank Sta=529.5,548.5
XS Rating Curve= 0 ,0
Exp/Cntr(USF)=0,0
Exp/Cntr=0.3,0.1

Type RM Length L Ch R = 1 ,3992    ,374.3,374.3,374.3
XS GIS Cut Line= 3
2203554.50274079633974.6505471932204123.88528029  634341.4642986
2204419.52621426634377.050707318
#Sta/Elev= 30
       0 2451.06    92.4 2423.49   101.9 2417.03   115.5  2412.7   122.8 2406.52
   136.2 2404.85   163.8 2394.18   225.6 2364.11   273.2 2348.27   282.7 2343.32
   353.2 2325.85   373.1 2314.92   392.2 2312.52   411.1 2314.91   515.52315.557
   537.52314.609   558.7 2312.49   625.1 2319.14   658.6 2325.37   681.6 2333.42
   705.8 2337.47     734 2352.31   774.3 2369.05     820 2384.74   835.5  2393.5
   846.8 2396.99   862.9 2408.48   907.2 2427.97   919.3 2430.34   975.1 2458.82
#Mann= 1 ,-1,0
       0   -9999       0
Bank Sta=515.5,537.5
XS Rating Curve= 0 ,0
Exp/Cntr(USF)=0,0
Exp/Cntr=0.3,0.1

Type RM Length L Ch R = 1 ,3617    ,432.7,432.7,432.7
XS GIS Cut Line= 2
2203423.10677014634464.6480210872204389.41463765634533.083422469
#Sta/Elev= 30
       0 2455.21    49.2 2432.26    73.3 2417.74    85.3 2408.27    97.3 2406.06
   125.4 2392.89   157.5 2382.97   197.6 2362.31   245.7 2347.28   257.7 2346.27
   309.8 2329.25     370 2317.08   450.9 2313.52     471 2311.83   492.1 2306.53
   534.4 2304.92   572.52306.394   586.5 2307.84   606.6 2319.94   617.7 2323.27
   662.7 2329.21   682.8 2335.11   694.8 2341.29   710.8 2343.09   726.9 2351.59
   754.2 2361.29   839.2 2389.47   879.3 2400.62   931.4 2420.76   968.7 2438.25
#Mann= 1 ,-1,0
       0   -9999       0
Bank Sta=572.5,617.7
XS Rating Curve= 0 ,0
Exp/Cntr(USF)=0,0
Exp/Cntr=0.3,0.1

Type RM Length L Ch R = 1 ,3185    ,350.1,350.1,350.1
XS GIS Cut Line= 2
2203360.14620087634705.5406339512204282.65541149634834.199188549
#Sta/Elev= 30
       0  2404.8    24.3 2399.32    60.6 2396.04      97 2388.29   109.6 2382.48
   123.8 2379.22   202.3  2343.5   218.1 2334.49   234.3 2331.43   254.5 2322.61
   294.9 2309.23   351.4 2295.76   391.8 2299.14   456.72298.287   464.5 2297.26
   484.7 2300.24   504.9 2306.05   545.3 2308.99   589.7 2315.43   631.92326.887
   666.1 2337.44   682.6 2345.02   698.7 2347.67     723  2357.7   775.5 2369.33
   811.4 2382.61     836 2395.81   844.1 2396.52   872.4 2408.28   931.4 2422.89
#Mann= 1 ,-1,0
       0   -9999       0
Bank Sta=456.7,631.9
XS Rating Curve= 0 ,0
Exp/Cntr(USF)=0,0
Exp/Cntr=0.3,0.1

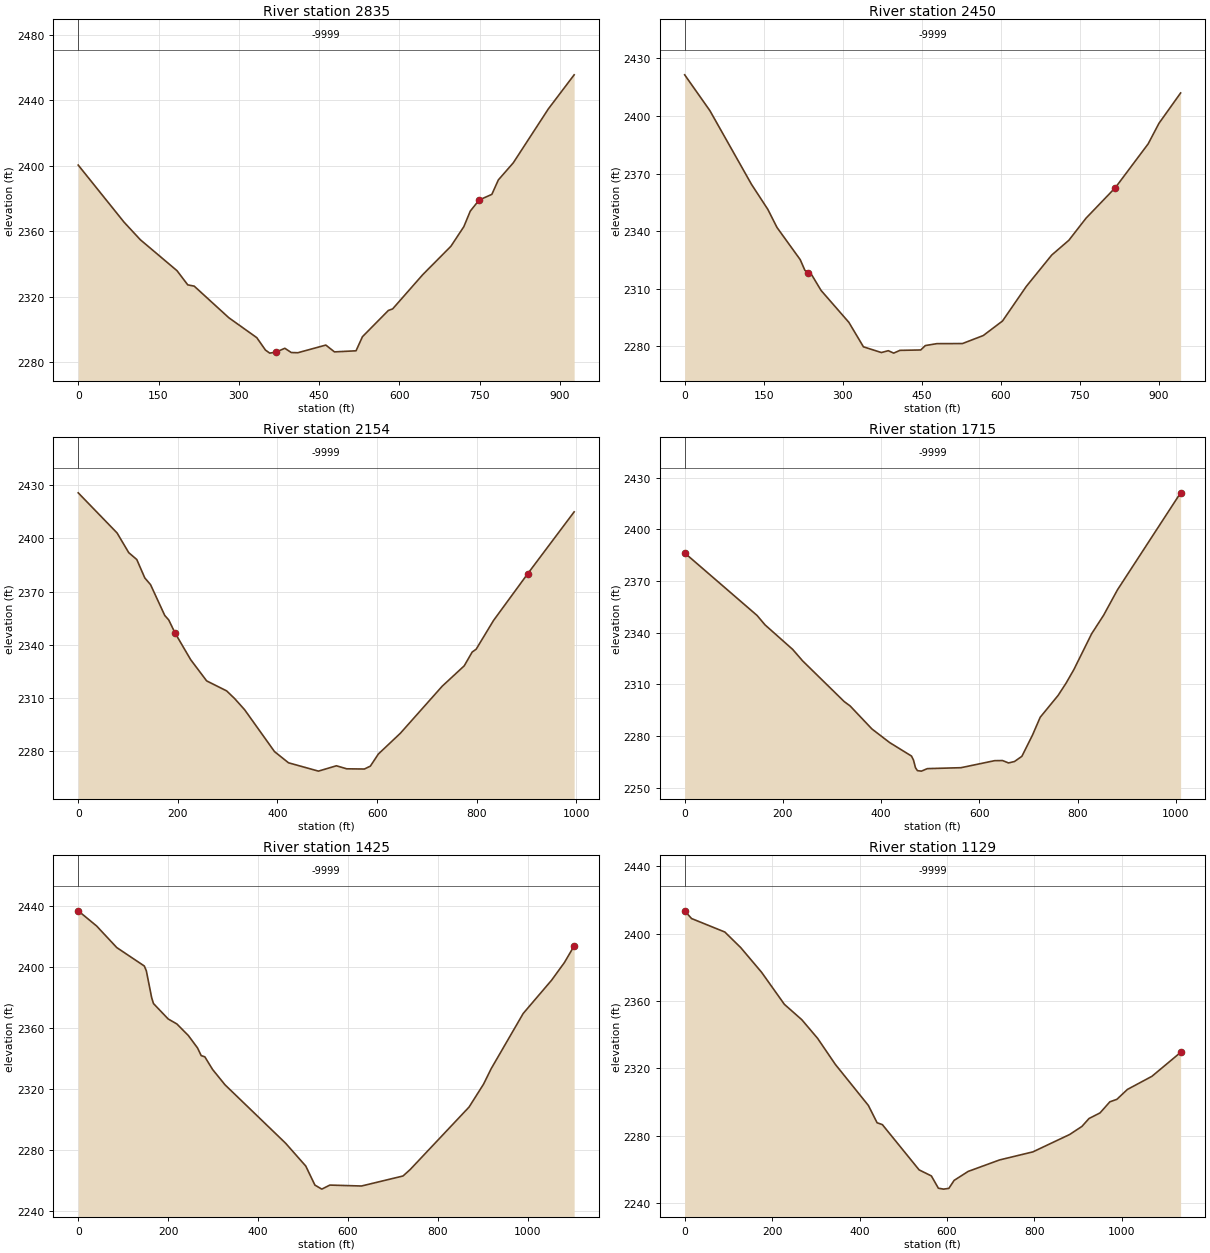
Type RM Length L Ch R = 1 ,2835    ,385,385,385
XS GIS Cut Line= 2
2203236.96247838635036.7679766392204156.73427295 635146.26461885
#Sta/Elev= 30
       0 2400.27    85.5 2365.45     116 2354.68   184.5 2335.78   204.6 2327.12
   216.7 2326.33   281.2 2307.06   333.6 2294.85   349.7  2287.3   357.7 2285.42
   369.42286.029   385.9 2288.38     398 2285.79   410.2 2285.66   462.5 2290.34
   478.6 2286.18   518.9 2286.84   530.9 2295.45   579.3 2311.48   587.3 2312.43
   643.7 2333.41   696.1 2350.68   720.3 2362.67   732.3 2372.16   748.82378.924
   772.6 2382.38   784.7 2391.19   812.6 2401.64     878 2434.52   926.3 2455.39
#Mann= 1 ,-1,0
       0   -9999       0
Bank Sta=369.4,748.8
XS Rating Curve= 0 ,0
Exp/Cntr(USF)=0,0
Exp/Cntr=0.3,0.1

Type RM Length L Ch R = 1 ,2450    ,295.8,295.8,295.8
XS GIS Cut Line= 3
2203176.73932516635170.9013633482203691.37354355635406.319144101
2204060.92471102635472.017129428
#Sta/Elev= 30
       0 2421.48    47.8 2402.82   126.9 2364.31   157.7 2351.35   175.3 2341.82
   219.3 2325.06   228.1 2319.54   234.32317.979   241.3 2317.05   258.9 2308.99
   311.7 2292.33   339.3 2279.58   373.3  2276.6   386.5 2277.55   396.7 2276.29
   408.5 2277.73     448 2277.94   456.8 2280.24   478.8 2281.24   527.2 2281.28
   566.7 2285.46   603.3 2293.06   648.4 2311.09   696.7 2327.47   729.2 2335.17
   761.7 2346.67   817.6 2362.68   879.6 2385.42   900.2 2396.18   941.3 2412.02
#Mann= 1 ,-1,0
       0   -9999       0
Bank Sta=234.3,817.6
XS Rating Curve= 0 ,0
Exp/Cntr(USF)=0,0
Exp/Cntr=0.3,0.1

Type RM Length L Ch R = 1 ,2154    ,438.8,438.8,438.8
XS GIS Cut Line= 2
2203050.81818662635614.3627643022204044.50021468635554.139611086
#Sta/Elev= 30
       0 2425.75      78 2403.09   101.5 2391.94   117.6 2388.08   133.6 2377.72
   145.2 2373.89   173.7 2356.52   181.7 2353.97   194.42346.594   225.8 2331.51
   257.8 2319.56   297.9 2313.91   313.9 2309.59     334 2303.28   394.1 2279.59
   422.1  2273.3   482.2 2268.59   518.3 2271.61   538.9  2269.9   574.4 2269.78
   586.4  2271.4   602.5 2278.25   646.5 2289.93   730.7 2316.56   774.8 2328.04
   790.8 2335.84   798.8 2337.44   833.6 2353.64   902.42380.104   995.5    2415
#Mann= 1 ,-1,0
       0   -9999       0
Bank Sta=194.4,902.4
XS Rating Curve= 0 ,0
Exp/Cntr(USF)=0,0
Exp/Cntr=0.3,0.1

Type RM Length L Ch R = 1 ,1715    ,289.7,289.7,289.7
XS GIS Cut Line= 2
2202965.95828891635852.5179611112203967.85256514635978.439099654
#Sta/Elev= 30
       0  2386.3   147.4 2350.04   163.7 2344.55   219.9 2330.34   240.1 2323.71
   324.9 2300.06   336.8 2297.57   381.2 2284.21   417.5 2276.28   461.8 2268.49
   465.9 2266.15   469.9 2261.74   473.9 2260.02     482 2259.74   494.1 2261.19
   562.6 2261.73   631.1 2265.81   647.2 2265.87   659.4 2264.49   671.5 2265.32
   686.6 2268.34   708.1 2280.59   723.9 2290.99   760.2 2303.61   776.3 2310.65
   792.4 2318.63   828.7 2339.48   852.9 2350.12   881.1 2364.861009.776 2421.17
#Mann= 1 ,-1,0
       0   -9999       0
Bank Sta=0,1009.776
XS Rating Curve= 0 ,0
Exp/Cntr(USF)=0,0
Exp/Cntr=0.3,0.1

Type RM Length L Ch R = 1 ,1425    ,296.3,296.3,296.3
XS GIS Cut Line= 2
2202892.04805541  636287.76711392203973.32739725636068.773829478
#Sta/Elev= 30
       0  2437.1    40.9 2427.15    85.8 2412.94   147.1 2400.82   151.6  2397.6
   163.4 2380.01   167.5 2376.14   200.1 2366.03   219.5 2362.74     245 2355.14
   265.4    2347   273.6 2341.95   281.7 2341.14   298.8 2332.88   326.6 2322.74
   461.3 2284.38   506.2 2269.35   526.6 2256.83   541.9 2254.19   559.8 2256.85
   630.2 2256.24   722.5 2262.82   738.8 2267.17   869.4 2308.11   901.7 2323.18
   918.6 2333.32   989.9 2369.64  1053.1 2391.52  1081.7 2403.171103.233 2414.05
#Mann= 1 ,-1,0
       0   -9999       0
Bank Sta=0,1103.233
XS Rating Curve= 0 ,0
Exp/Cntr(USF)=0,0
Exp/Cntr=0.3,0.1

Type RM Length L Ch R = 1 ,1129    ,,,
XS GIS Cut Line= 2
 2202856.4616467636435.5875808852203989.75189358636482.123653824
#Sta/Elev= 30
       0 2413.51    15.7 2408.93    91.8 2400.93   128.2 2391.67   175.9 2377.02
   228.1 2357.97   267.9 2348.85     304  2337.8   344.5 2322.35   420.1 2297.95
   440.1 2287.66   452.1 2286.57   536.2 2259.68   564.2 2256.11   580.2 2248.81
   592.2 2248.26   604.2 2248.71   616.2 2253.44   648.3 2258.77   720.3  2265.6
   796.4 2270.38   880.5  2280.7   908.5 2285.49   924.8  2290.2   949.9 2293.51
   972.5 2300.12   988.5 2301.58  1012.5 2307.45  1068.6 2315.241134.245 2329.45
#Mann= 1 ,-1,0
       0   -9999       0
Bank Sta=0,1134.245
XS Rating Curve= 0 ,0
Exp/Cntr(USF)=0,0
Exp/Cntr=0.3,0.1
LCMann Table=0

Chan Stop Cuts=-1
Use User Specified Reach Order=0
Composite Channel Slope=5